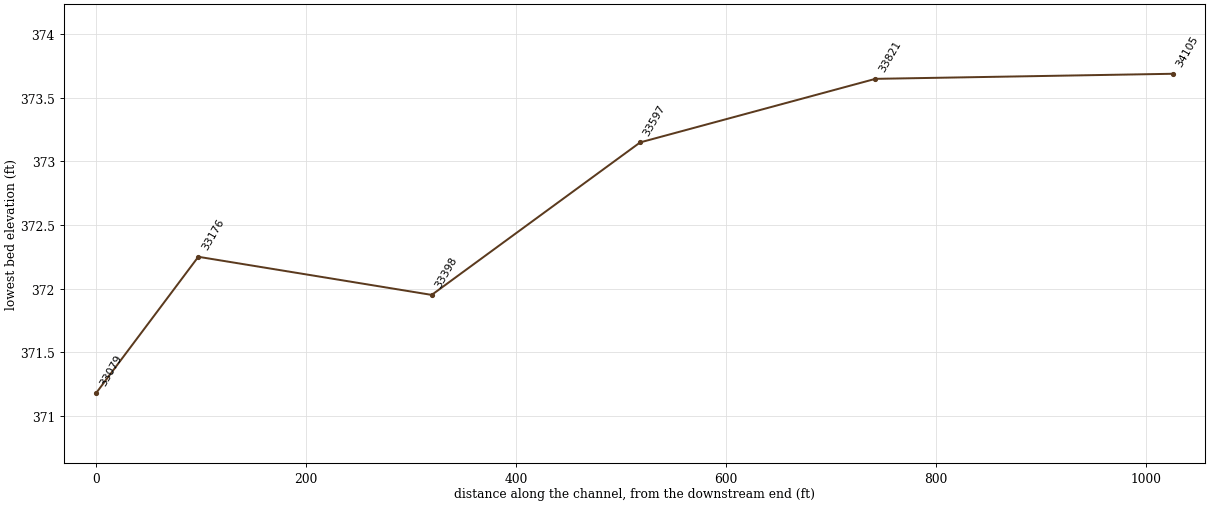
--- CarrollCo.prj (project) ---

Proj Title=Carroll Co
Current Plan=p04
Default Exp/Contr=0.3,0.1
English Units
Geom File=g01
Geom File=g02
Geom File=g03
Geom File=g04
Flow File=f01
Plan File=p01
Plan File=p02
Plan File=p03
Plan File=p04
Y Axis Title=Elevation
X Axis Title(PF)=Main Channel Distance
X Axis Title(XS)=Station
BEGIN DESCRIPTION:
END DESCRIPTION:
DSS File=dss
DSS Export Rating Curves= 0
DSS Export Rating Curve Sorted= 0
DSS Export Volume Flow Curves= 0
DXF Filename=..\..\TDOT - Bridges - HEC-RAS\HEC-RAS\Carroll Co\Carroll Co HEC-RAS\CarrollCo.
DXF OffsetX= 0
DXF OffsetY= 0
DXF ScaleX= 1
DXF ScaleY= 10

--- CarrollCo.p04 (plan) ---

Plan Title=PROPOSED-Revised
Program Version=4.10
Short Identifier=Proposed-Revised
Geom File=g04
Flow File=f01
Subcritical Flow
K Sum by GR= 0
Std Step Tol= 0.01
Critical Tol= 0.01
Num of Std Step Trials= 20
Max Error Tol= 0.3
Flow Tol Ratio= 0.001
Split Flow NTrial= 30
Split Flow Tol= 0.02
Split Flow Ratio= 0.02
Log Output Level= 0
Friction Slope Method= 1
Unsteady Friction Slope Method= 2
Unsteady Bridges Friction Slope Method= 1
Parabolic Critical Depth
Global Vel Dist= 0 , 0 , 0
Global Log Level= 0
CheckData=True
Encroach Param=-1 ,0,0, 0
Computation Interval=1MIN
Output Interval=1HOUR
Run HTab= 0
Run UNet= 0
Run PostProcess= 0
Run WQNet= 0
UNET Theta= 1
UNET Theta Warmup= 1
UNET ZTol= 0.02
UNET ZSATol= 0.02
UNET MxIter= 20
UNET MaxInSteps= 0
UNET DtIC= 0
UNET DtMin= 0
UNET MaxCRTS= 20
UNET WFStab= 2
UNET SFStab= 1
UNET WFX= 1
UNET SFX= 1
UNET DSS MLevel= 4
UNET DZMax Abort= 100
UNET Convert EG Bridges= 0
UNET Use Existing IB Tables=-1
UNET Froude Reduction=False
UNET Froude Limit= 0.8
UNET Froude Power= 4
UNET Time Slicing=0,0, 5
UNET Junction Losses=0
Instantaneous Interval=1HOUR
Write IC File= 0
Write IC File at Sim End=0
Echo Input=False
Echo Parameters=False
Echo Output=False
Write Detailed= 0
WQ AD Non Conservative
WQ ULTIMATE=-1
WQ Max Comp Step=1HOUR
WQ Output Interval=15MIN
WQ Output Selected Increments= 0
WQ Output face flow=0
WQ Output face velocity=0
WQ Output face area=0
WQ Output face dispersion=0
WQ Output cell volume=0
WQ Output cell surface area=0
WQ Output cell continuity=0
WQ Output cumulative cell continuity=0
WQ Output face conc=0
WQ Output face dconc_dx=0
WQ Output face courant=0
WQ Output face peclet=0
WQ Output face adv mass=0
WQ Output face disp mass=0
WQ Output cell mass=0
WQ Output cell source sink temp=0
WQ Output cell source sink nsm=0
WQ Output MaxMinRange=-1
WQ Daily Max Min Mean=-1
WQ Daily Range=0
WQ Daily Time=0
WQ Create Restart=0
WQ Fixed Restart=0
WQ System Summary=0
WQ Use Fixed Temperature=0
Sorting and Armoring Iterations= 10
XS Update Threshold= 0.02
Hydraulics Update Threshold= 0.02
Energy Slope Method= 1
Volume Change Method= 1
XS Weighting Method= 0
Number of US Weighted Cross Sections= 1
Number of DS Weighted Cross Sections= 1
Upstream XS Weight=0
Main XS Weight=1
Downstream XS Weight=0
Number of DS XS's Weighted with US Boundary= 1
Upstream Boundary Weight= 1
Weight of XSs Associated with US Boundary= 0
Number of US XS's Weighted with DS Boundary= 1
Downstream Boundary Weight= 0.5
Weight of XSs Associated with DS Boundary= 0.5
Sediment Output Level= 3
Mass or Volume Output= 0
Output Increment Type= 1
Profile and TS Output Increment= 1
XS Output Flag= 0
XS Output Increment= 10
Disregard all LS=0
Disregard all Conn=0
Disregard all Breaches=0
Disregard all Pumps=0

--- CarrollCo.p01 (plan) ---

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Plan Title=EXISTING
Program Version=5.06
Short Identifier=EXIST
Geom File=g01
Flow File=f01
Mapping Interval=1HOUR
Computation Time Step Use Courant=        0
Computation Time Step Use Time Series=    0
Computation Time Step Count To Double=0
Computation Time Step Max Doubling=0
Computation Time Step Max Halving=0
Computation Time Step Residence Courant=0
Run Sediment= 0
Run RASMapper= 0
UNET Max Iter WO Improvement= 0
UNET 1D Methodology=Finite Difference
UNET Pardiso=0
UNET D1 Cores= 0
UNET D2 Coriolis=0
UNET D2 Cores= 0
UNET D2 Theta= 1
UNET D2 Theta Warmup= 1
UNET D2 Z Tol= 0.01
UNET D2 Volume Tol= 0.01
UNET D2 Max Iterations= 20
UNET D2 Equation= 0
UNET D2 RampUpFraction=0.1
UNET D2 TimeSlices= 1
UNET D2 BCVolumeCheck=0
UNET D1D2 MaxIter= 0
UNET D1D2 ZTol=0.01
UNET D1D2 QTol=0.1
UNET D1D2 MinQTol=1
Write IC File at Fixed DateTime=0
HDF Write Warmup=0
HDF Write Time Slices=0
HDF Flush=0
HDF Face Node Velocities=0
HDF Compression= 1
HDF Chunk Size= 1
HDF Spatial Parts= 1
HDF Use Max Rows=0
HDF Fixed Rows= 1
Calibration Method= 0
Calibration Iterations= 20
Calibration Max Change=0.05
Calibration Tolerance=0.2
Calibration Maximum=1.5
Calibration Minimum=0.5
Calibration Optimization Method= 1
WQ Output nsm pathways=0
WQ Output nsm derived pathways=0
WQ Write To DSS=0
Bed Roughness Predictor= 0
Sediment Retention Method= 0
Percentile Method= 0
Write Gradation File= 0
Read Gradation Hotstart= 0
Write HDF5 File= 1
Write Binary Output= 1
Write DSS Sediment File= 0
SV Curve= 0
Specific Gage Flag= 0

--- CarrollCo.p02 (plan) ---

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Plan Title=NATURAL
Program Version=5.06
Short Identifier=NATURAL
Geom File=g02
Flow File=f01
Mapping Interval=1HOUR
Computation Time Step Use Courant=        0
Computation Time Step Use Time Series=    0
Computation Time Step Count To Double=0
Computation Time Step Max Doubling=0
Computation Time Step Max Halving=0
Computation Time Step Residence Courant=0
Run Sediment= 0
Run RASMapper= 0
UNET Max Iter WO Improvement= 0
UNET 1D Methodology=Finite Difference
UNET Pardiso=0
UNET D1 Cores= 0
UNET D2 Coriolis=0
UNET D2 Cores= 0
UNET D2 Theta= 1
UNET D2 Theta Warmup= 1
UNET D2 Z Tol= 0.01
UNET D2 Volume Tol= 0.01
UNET D2 Max Iterations= 20
UNET D2 Equation= 0
UNET D2 RampUpFraction=0.1
UNET D2 TimeSlices= 1
UNET D2 BCVolumeCheck=0
UNET D1D2 MaxIter= 0
UNET D1D2 ZTol=0.01
UNET D1D2 QTol=0.1
UNET D1D2 MinQTol=1
Write IC File at Fixed DateTime=0
HDF Write Warmup=0
HDF Write Time Slices=0
HDF Flush=0
HDF Face Node Velocities=0
HDF Compression= 1
HDF Chunk Size= 1
HDF Spatial Parts= 1
HDF Use Max Rows=0
HDF Fixed Rows= 1
Calibration Method= 0
Calibration Iterations= 20
Calibration Max Change=0.05
Calibration Tolerance=0.2
Calibration Maximum=1.5
Calibration Minimum=0.5
Calibration Optimization Method= 1
WQ Output nsm pathways=0
WQ Output nsm derived pathways=0
WQ Write To DSS=0
Bed Roughness Predictor= 0
Sediment Retention Method= 0
Percentile Method= 0
Write Gradation File= 0
Read Gradation Hotstart= 0
Write HDF5 File= 1
Write Binary Output= 1
Write DSS Sediment File= 0
SV Curve= 0
Specific Gage Flag= 0

--- CarrollCo.p03 (plan) ---

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Plan Title=PROPOSED
Program Version=5.06
Short Identifier=PROPOSED
Geom File=g03
Flow File=f01
Mapping Interval=1HOUR
Computation Time Step Use Courant=        0
Computation Time Step Use Time Series=    0
Computation Time Step Count To Double=0
Computation Time Step Max Doubling=0
Computation Time Step Max Halving=0
Computation Time Step Residence Courant=0
Run Sediment= 0
Run RASMapper= 0
UNET Max Iter WO Improvement= 0
UNET 1D Methodology=Finite Difference
UNET Pardiso=0
UNET D1 Cores= 0
UNET D2 Coriolis=0
UNET D2 Cores= 0
UNET D2 Theta= 1
UNET D2 Theta Warmup= 1
UNET D2 Z Tol= 0.01
UNET D2 Volume Tol= 0.01
UNET D2 Max Iterations= 20
UNET D2 Equation= 0
UNET D2 RampUpFraction=0.1
UNET D2 TimeSlices= 1
UNET D2 BCVolumeCheck=0
UNET D1D2 MaxIter= 0
UNET D1D2 ZTol=0.01
UNET D1D2 QTol=0.1
UNET D1D2 MinQTol=1
Write IC File at Fixed DateTime=0
HDF Write Warmup=0
HDF Write Time Slices=0
HDF Flush=0
HDF Face Node Velocities=0
HDF Compression= 1
HDF Chunk Size= 1
HDF Spatial Parts= 1
HDF Use Max Rows=0
HDF Fixed Rows= 1
Calibration Method= 0
Calibration Iterations= 20
Calibration Max Change=0.05
Calibration Tolerance=0.2
Calibration Maximum=1.5
Calibration Minimum=0.5
Calibration Optimization Method= 1
WQ Output nsm pathways=0
WQ Output nsm derived pathways=0
WQ Write To DSS=0
Bed Roughness Predictor= 0
Sediment Retention Method= 0
Percentile Method= 0
Write Gradation File= 0
Read Gradation Hotstart= 0
Write HDF5 File= 1
Write Binary Output= 1
Write DSS Sediment File= 0
SV Curve= 0
Specific Gage Flag= 0

--- CarrollCo.f01 (steady flow) ---

Flow Title=CarrollCoFlowData
Program Version=5.06
Number of Profiles= 7
Profile Names=Q2,Q5,Q10,Q25,Q50,Q100,Q500
River Rch & RM=Reedy Creek,Reedy Creek     ,34105
    2430    3660    4480    5530    6300    7050    8860
Boundary for River Rch & Prof#=Reedy Creek,Reedy Creek     , 1
Up Type= 0
Dn Type= 3
Dn Slope=0.0015
Boundary for River Rch & Prof#=Reedy Creek,Reedy Creek     , 2
Up Type= 0
Dn Type= 3
Dn Slope=0.0015
Boundary for River Rch & Prof#=Reedy Creek,Reedy Creek     , 3
Up Type= 0
Dn Type= 3
Dn Slope=0.0015
Boundary for River Rch & Prof#=Reedy Creek,Reedy Creek     , 4
Up Type= 0
Dn Type= 3
Dn Slope=0.0015
Boundary for River Rch & Prof#=Reedy Creek,Reedy Creek     , 5
Up Type= 0
Dn Type= 3
Dn Slope=0.0015
Boundary for River Rch & Prof#=Reedy Creek,Reedy Creek     , 6
Up Type= 0
Dn Type= 3
Dn Slope=0.0015
Boundary for River Rch & Prof#=Reedy Creek,Reedy Creek     , 7
Up Type= 0
Dn Type= 3
Dn Slope=0.0015
DSS Import GetInterval= 0
DSS Import GetPeak= 0
DSS Import FillOption= 0

--- CarrollCo.g04 (geometry) ---

Geom Title=PROPOSED-Revised
Program Version=4.10

River Reach=Reedy Creek     ,Reedy Creek
Reach XY= 4
0.76244813278008 0.47925311203320.28319502074689 0.5103734439834
-0.08402489626550.42116182572614-0.19106506430670.39314061397015

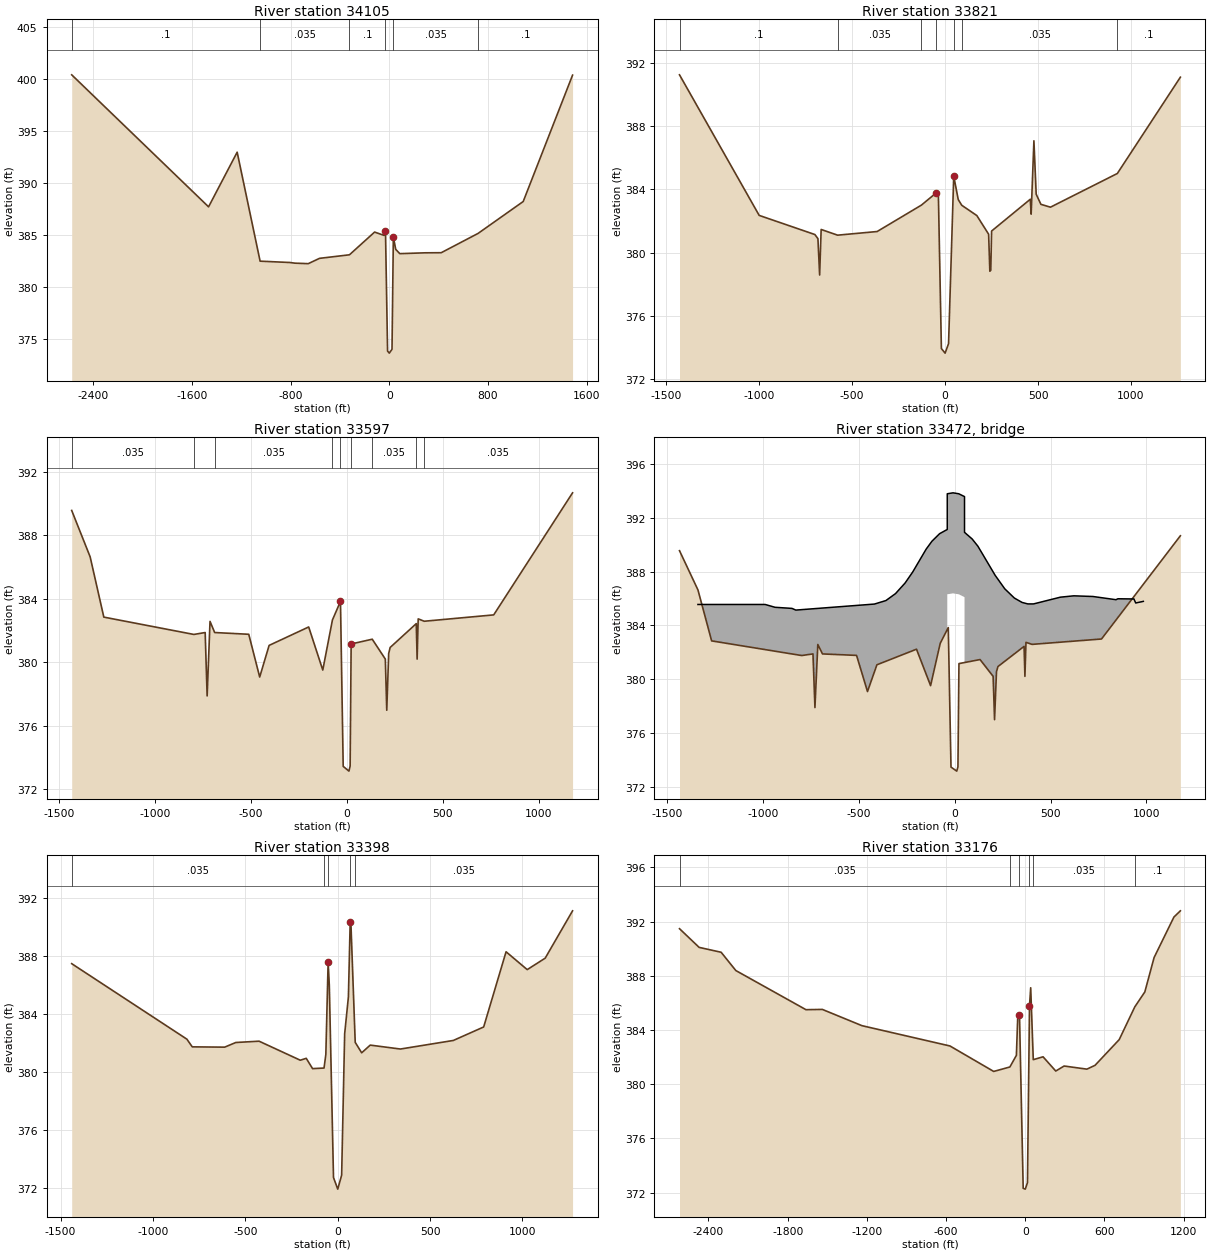
Type RM Length L Ch R = 1 ,34105   ,285.63,283.68,284.55
BEGIN DESCRIPTION:
STA 34105 - LiDAR 1
END DESCRIPTION:
#Sta/Elev= 25
-2576.27  400.38-1466.03  387.72-1234.01  392.96-1047.91  382.51 -804.63  382.38
 -767.74  382.32 -657.56  382.27 -565.74  382.78 -323.06  383.12 -119.06   385.3
  -42.19  384.98  -37.07  385.23  -30.74  385.39  -13.85  373.89       0  373.69
   22.13  374.06   33.01  384.83   46.85  383.97   52.33  383.64   85.48  383.23
  292.23  383.31  421.25  383.32  720.25  385.17 1086.54  388.23 1486.89  400.35
#Mann= 6 ,-1 , 0
-2576.27      .1       0-1047.91    .035       0 -323.06      .1       0
  -30.74    .045       0   33.01    .035       0  720.25      .1       0
#XS Ineff= 2 , 0
         -119.06           95.83
Permanent Ineff=
       F       F
Bank Sta=-30.74,33.01
XS Rating Curve= 0 ,0
Exp/Cntr=0.3,0.1

Type RM Length L Ch R = 1 ,33821   ,228.05,224.2,221.45
BEGIN DESCRIPTION:
STA 33821 - CS 4 - UPSTRFLOODPL
END DESCRIPTION:
#Sta/Elev= 30
-1429.34  391.25-1000.54  382.36 -700.84  381.15 -684.47  380.89  -675.2  378.59
  -667.1  381.47 -578.61  381.11 -365.78  381.34 -127.58  383.01  -49.37  383.77
  -36.39  383.76  -20.01  373.94       0  373.65   18.51  374.25   46.35  384.84
   70.78  383.36   89.64     383  170.72  382.35  234.17  381.17  240.78  378.83
  245.78  378.89  250.12  381.37  458.34  383.38  463.02  382.44   477.9  387.08
  490.12   383.7  515.56  383.06  566.94  382.88  926.82  385.01 1266.06   391.1
#Mann= 7 ,-1 , 0
-1429.34      .1       0 -578.61    .035       0 -127.58      .1       0
  -49.37    .045       0   46.35      .1       0   89.64    .035       0
  926.82      .1       0
#XS Ineff= 2 , 0
         -119.06           95.83
Permanent Ineff=
       F       F
Bank Sta=-49.37,46.35
XS Rating Curve= 0 ,0
Exp/Cntr=0.5,0.3

Type RM Length L Ch R = 1 ,33597   ,198.08,198.64,202.04
BEGIN DESCRIPTION:
STA 33597 - CS 3
END DESCRIPTION:
#Sta/Elev= 30
-1435.15  389.55-1338.92  386.63-1267.64  382.84 -798.09  381.75 -739.03  381.87
 -728.78  377.88 -713.71  382.57 -689.44  381.87  -511.7  381.76 -454.64  379.07
 -405.54  381.06  -199.1  382.22 -125.62  379.51  -75.24  382.66  -33.33  383.83
  -19.13  373.45   10.87  373.15   17.07  373.47   22.36  381.15  132.39  381.45
  200.59   380.2  208.07  376.98  218.13  380.55  225.81  380.93  361.96  382.43
  366.45   380.2  372.03  382.73  403.47  382.58  765.93  382.98 1177.22  390.66
#Mann= 9 ,-1 , 0
-1435.15    .035       0 -798.09      .1       0 -689.44    .035       0
  -75.24      .1       0  -33.33    .045       0   22.36      .1       0
  132.39    .035       0  361.96      .1       0  403.47    .035       0
#XS Ineff= 2 , 0
         -119.06           95.83
Permanent Ineff=
       F       F
Bank Sta=-33.33,22.36
XS Rating Curve= 0 ,0
Exp/Cntr=0.5,0.3

Type RM Length L Ch R = 3 ,33472   ,,,
Bridge Culvert--1,0,-1,-1, 0
Deck Dist Width WeirC Skew NumUp NumDn MinLoCord MaxHiCord MaxSubmerge Is_Ogee
99.485,29.25,2.6,0, 35, 35, , , 0.98, 0, 1.85,2,,
   -1339 -988.62 -936.86 -848.62-828.621 -418.62 -358.62 -308.62 -258.62 -218.62
 -148.62 -118.62  -78.62 -38.621  -38.62   -8.62   21.38   51.38  51.381   91.38
  121.38  211.38  261.38  311.38  351.38  381.38  411.38  551.38  621.38  721.38
  841.38  851.38  934.78  944.28   984.1
  385.55  385.55  385.34 385.258 385.132  385.58 385.841 386.357 387.146 387.972
 389.669 390.255 390.817  391.13 393.786 393.856 393.786 393.575 390.919 390.419
  389.88 387.714 386.714 386.027 385.703 385.591 385.591 386.093 386.193 386.143
 385.905 385.974  385.96  385.66  385.78
     360     360     360     360     360     360     360     360     360     360
     360     360     360     360 386.307 386.378 386.307 386.096     360     360
     360     360     360     360     360     360     360     360     360     360
     360     360     360     360     360
   -1339 -988.62 -936.86 -848.62-828.621 -418.62 -358.62 -308.62 -258.62 -218.62
 -148.62 -118.62  -78.62 -38.621  -38.62   -8.62   21.38   51.38  51.381   91.38
  121.38  211.38  261.38  311.38  351.38  381.38  411.38  551.38  621.38  721.38
  841.38  851.38  934.78  944.28   984.1
  385.55  385.55  385.34 385.258 385.132  385.58 385.841 386.357 387.146 387.972
 389.669 390.255 390.817  391.13 393.786 393.856 393.786 393.575 390.919 390.419
  389.88 387.714 386.714 386.027 385.703 385.591 385.591 386.093 386.193 386.143
 385.905 385.974  385.96  385.66  385.78
     360     360     360     360     360     360     360     360     360     360
     360     360     360     360 386.307 386.378 386.307 386.096     360     360
     360     360     360     360     360     360     360     360     360     360
     360     360     360     360     360
BR Coef=-1 , 0 , 0 ,, 0 ,,,0.8,-1,,0,
WSPro=,,,, 1 ,,,, 0 ,,,, 0 ,,,,-1 ,-1 ,-1 , 0 , 0 , 0 , 0 , 0
BC Design=,, 0 ,, 0 ,,,,,,
BC Use User HTab Curves=0
BC User HTab FreeFlow(D)= 0

Type RM Length L Ch R = 1 ,33398   ,227.28,222.42,224.4
BEGIN DESCRIPTION:
STA 33398 - CS 2
END DESCRIPTION:
#Sta/Elev= 30
   -1440  387.48 -816.65  382.28 -787.47  381.75 -612.12  381.73 -551.69  382.05
 -425.83  382.14 -202.77  380.83  -170.5  380.96 -136.28  380.25  -74.24  380.29
  -64.46  381.22  -52.06  387.58   -45.6  385.97  -22.98  372.75       0  371.95
   21.08  372.91   37.44  382.65   57.68  385.19   67.44  390.38   71.48  390.19
   94.56  382.06   129.5  381.34  175.83  381.87  339.35   381.6  625.43  382.19
  789.88  383.12  911.06   388.3 1025.59  387.07 1122.88  387.86 1271.02  391.12
#Mann= 5 ,-1 , 0
   -1440    .035       0  -74.24      .1       0  -52.06    .045       0
   67.44      .1       0   94.56    .035       0
#XS Ineff= 2 , 0
         -119.06           95.83
Permanent Ineff=
       F       F
Bank Sta=-52.06,67.44
XS Rating Curve= 0 ,0
Exp/Cntr=0.5,0.3

Type RM Length L Ch R = 1 ,33176   ,92.19,97.17,105.42
BEGIN DESCRIPTION:
STA 33176 - CS 1 - DSFLOODPL
END DESCRIPTION:
#Sta/Elev= 30
-2619.17  391.48 -2470.4   390.1-2303.79  389.74-2192.52  388.39-1661.14   385.5
-1537.23  385.52 -1237.2  384.32 -570.43  382.82  -239.2  380.94 -116.53  381.27
  -67.31  382.13  -56.18  385.23  -43.85  385.11  -15.83  372.31       0  372.25
   16.58  372.73   31.89  385.76   40.99  387.12   60.56  381.81  134.74  382.02
  230.82  380.97   294.2  381.34  466.51  381.11  528.26  381.39   711.5  383.29
  829.65  385.71  905.49  386.81  975.76  389.35 1125.87  392.34 1174.77   392.8
#Mann= 6 ,-1 , 0
-2619.17    .035       0 -116.53      .1       0  -43.85    .045       0
   31.89      .1       0   60.56    .035       0  829.65      .1       0
#XS Ineff= 2 , 0
         -119.06           95.83
Permanent Ineff=
       F       F
Bank Sta=-43.85,31.89
XS Rating Curve= 0 ,0
Exp/Cntr=0.3,0.1

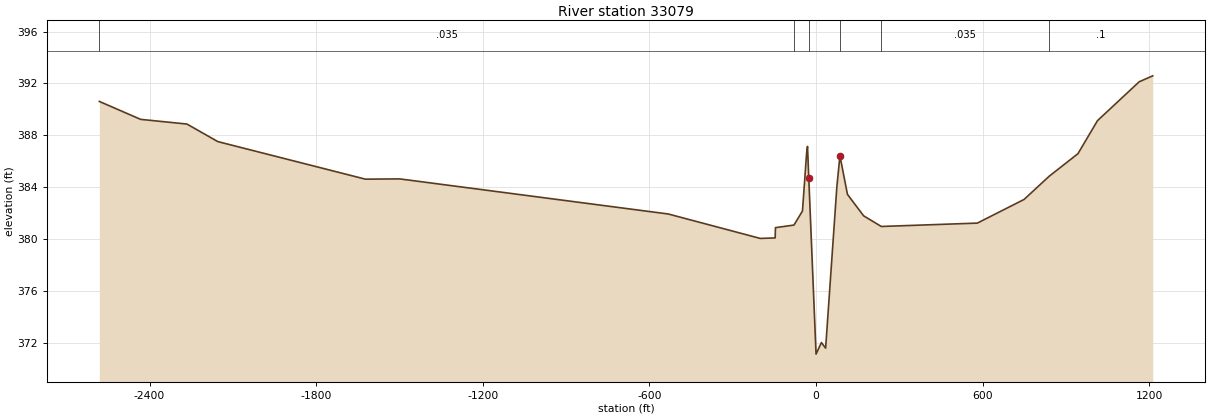
Type RM Length L Ch R = 1 ,33079   ,500,500,500
BEGIN DESCRIPTION:
STA 33079 - DSXSEC
END DESCRIPTION:
#Sta/Elev= 30
-2580.66  390.62-2431.89  389.24-2265.28  388.88-2154.01  387.53-1622.63  384.64
-1498.72  384.66 -531.92  381.96 -200.69  380.08 -147.21  380.12 -146.26  380.91
  -79.46  381.11  -48.91  382.19  -34.09  386.61  -30.78  387.16  -26.18  384.72
       0  371.18   19.27  372.07   34.49  371.64    74.9  384.05   85.98  386.44
  113.08  383.47  171.27  381.82  234.99     381  580.78  381.26  749.03  383.08
  839.68  384.87  943.02   386.6 1013.29  389.14  1163.4  392.13  1212.3  392.59
#Mann= 6 ,-1 , 0
-2580.66    .035       0  -79.46      .1       0  -26.18    .045       0
   85.98      .1       0  234.99    .035       0  839.68      .1       0
#XS Ineff= 2 , 0
         -119.06           95.83
Permanent Ineff=
       F       F
Bank Sta=-26.18,85.98
XS Rating Curve= 0 ,0
Exp/Cntr=0.3,0.1

Chan Stop Cuts=-1
Use User Specified Reach Order=0
Composite Channel Slope=5

--- CarrollCo.g01 (geometry) ---

Geom Title=EXISTING
Program Version=5.06

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
River Reach=Reedy Creek     ,Reedy Creek

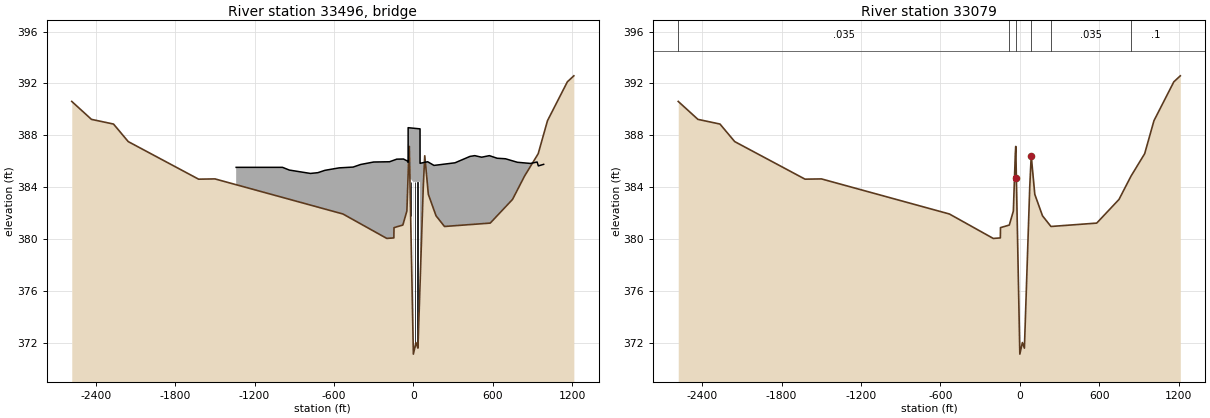
Type RM Length L Ch R = 3 ,33496   ,,,
Bridge Culvert--1,0,-1,-1, 0
Deck Dist Width WeirC Skew NumUp NumDn MinLoCord MaxHiCord MaxSubmerge Is_Ogee
90.1,22,2.6,0, 33, 33, , , 0.98, 0, 1.85,2,,
   -1339 -988.62 -936.86  -777.4 -721.54 -668.49  -560.1 -455.41 -398.31 -300.12
 -180.23 -125.48  -74.63  -44.41  -39.65  -39.62   50.38   50.49  107.98  155.31
  165.32  314.61   427.4  463.56  515.55   574.1  632.81  695.83  785.64  884.71
  934.78  944.28   984.1
  385.55  385.55  385.34  385.08  385.14  385.32  385.51  385.57  385.77  385.96
  385.98  386.18  386.19  386.03  385.94   388.6  388.51  385.86  385.98   385.7
  385.71   385.9  386.39  386.45  386.33  386.45  386.25  386.21  385.94  385.85
  385.96  385.66  385.78
     360     360     360     360     360     360     360     360     360     360
     360     360     360     360     360  384.43  384.43     360     360     360
     360     360     360     360     360     360     360     360     360     360
     360     360     360
   -1339 -988.62 -936.86  -777.4 -721.54 -668.49  -560.1 -455.41 -398.31 -300.12
 -180.23 -125.48  -74.63  -44.41  -39.65  -39.62   50.38   50.49  107.98  155.31
  165.32  314.61   427.4  463.56  515.55   574.1  632.81  695.83  785.64  884.71
  934.78  944.28   984.1
  385.55  385.55  385.34  385.08  385.14  385.32  385.51  385.57  385.77  385.96
  385.98  386.18  386.19  386.03  385.94   388.6  388.51  385.86  385.98   385.7
  385.71   385.9  386.39  386.45  386.33  386.45  386.25  386.21  385.94  385.85
  385.96  385.66  385.78
     360     360     360     360     360     360     360     360     360     360
     360     360     360     360     360  384.43  384.43     360     360     360
     360     360     360     360     360     360     360     360     360     360
     360     360     360
Pier Skew, UpSta & Num, DnSta & Num=  ,-20.62, 2 ,-20.62, 2 , 0 , 0 , 0 ,,
       2       2
     360  384.43
       2       2
     360  384.43
Pier Skew, UpSta & Num, DnSta & Num=  ,12.38, 2 ,12.38, 2 , 0 , 0 , 0 ,,
       2       2
     360  384.43
       2       2
     360  384.43
Pier Skew, UpSta & Num, DnSta & Num=  ,31.38, 2 ,31.38, 2 , 0 , 0 , 0 ,,
       1       1
     360  384.43
       1       1
     360  384.43
BR Coef=-1 , 0 , 0 ,, 0 ,,,0.8,-1,,0,
WSPro=,,,, 1 ,,,, 0 ,,,, 0 ,,,,-1 ,-1 ,-1 , 0 , 0 , 0 , 0 , 0
BC Design=,, 0 ,, 0 ,,,,,,
BC Use User HTab Curves=0
BC User HTab FreeFlow(D)= 0

Type RM Length L Ch R = 1 ,33079   ,500,500,500
BEGIN DESCRIPTION:
STA 33079 - DSXSEC
END DESCRIPTION:
#Sta/Elev= 30
-2580.66  390.62-2431.89  389.24-2265.28  388.88-2154.01  387.53-1622.63  384.64
-1498.72  384.66 -531.92  381.96 -200.69  380.08 -147.21  380.12 -146.26  380.91
  -79.46  381.11  -48.91  382.19  -34.09  386.61  -30.78  387.16  -26.18  384.72
       0  371.18   19.27  372.07   34.49  371.64    74.9  384.05   85.98  386.44
  113.08  383.47  171.27  381.82  234.99     381  580.78  381.26  749.03  383.08
  839.68  384.87  943.02   386.6 1013.29  389.14  1163.4  392.13  1212.3  392.59
#Mann= 6 ,-1 , 0
-2580.66    .035       0  -79.46      .1       0  -26.18    .045       0
   85.98      .1       0  234.99    .035       0  839.68      .1       0
#XS Ineff= 2 , 0
         -119.06           95.83
Permanent Ineff=
       F       F
Bank Sta=-26.18,85.98
XS Rating Curve= 0 ,0
Exp/Cntr=0.3,0.1
LCMann Table=0

--- CarrollCo.g02 (geometry) ---

Geom Title=NATURAL
Program Version=5.06

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
River Reach=Reedy Creek     ,Reedy Creek

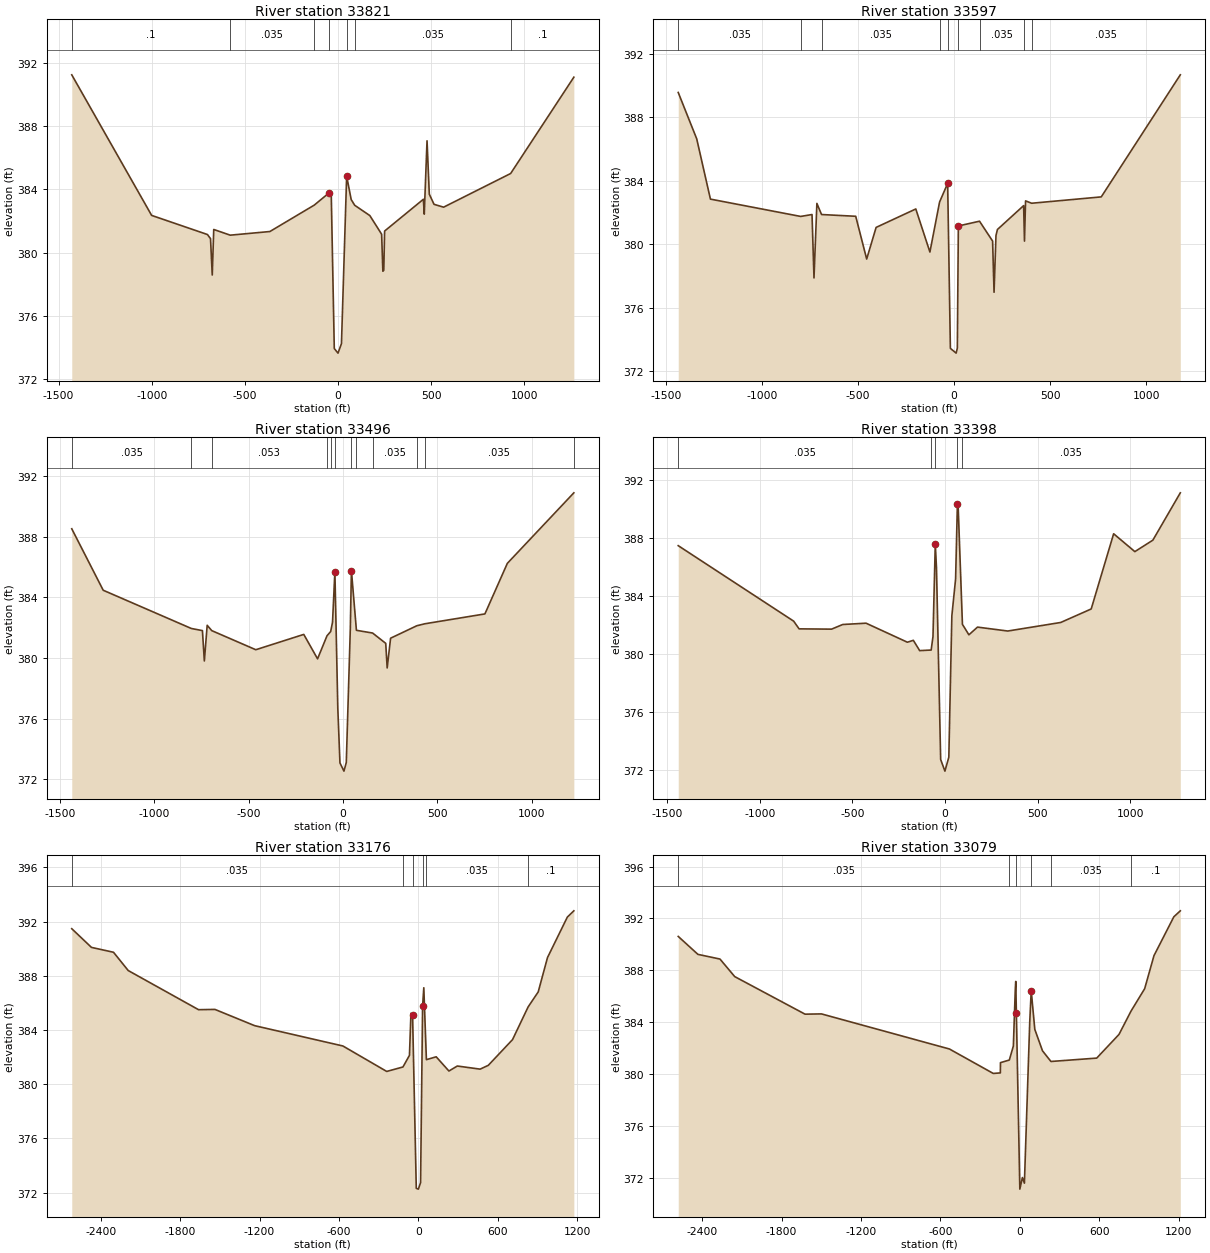
Type RM Length L Ch R = 1 ,33821   ,228.05,224.2,221.45
BEGIN DESCRIPTION:
STA 33821 - CS 4 - UPSTRFLOODPL
END DESCRIPTION:
#Sta/Elev= 30
-1429.34  391.25-1000.54  382.36 -700.84  381.15 -684.47  380.89  -675.2  378.59
  -667.1  381.47 -578.61  381.11 -365.78  381.34 -127.58  383.01  -49.37  383.77
  -36.39  383.76  -20.01  373.94       0  373.65   18.51  374.25   46.35  384.84
   70.78  383.36   89.64     383  170.72  382.35  234.17  381.17  240.78  378.83
  245.78  378.89  250.12  381.37  458.34  383.38  463.02  382.44   477.9  387.08
  490.12   383.7  515.56  383.06  566.94  382.88  926.82  385.01 1266.06   391.1
#Mann= 7 ,-1 , 0
-1429.34      .1       0 -578.61    .035       0 -127.58      .1       0
  -49.37    .045       0   46.35      .1       0   89.64    .035       0
  926.82      .1       0
#XS Ineff= 2 , 0
         -119.06           95.83
Permanent Ineff=
       F       F
Bank Sta=-49.37,46.35
XS Rating Curve= 0 ,0
Exp/Cntr=0.3,0.1

Type RM Length L Ch R = 1 ,33597   ,100.54,100.82,102.52
BEGIN DESCRIPTION:
STA 33597 - CS 3
END DESCRIPTION:
#Sta/Elev= 30
-1435.15  389.55-1338.92  386.63-1267.64  382.84 -798.09  381.75 -739.03  381.87
 -728.78  377.88 -713.71  382.57 -689.44  381.87  -511.7  381.76 -454.64  379.07
 -405.54  381.06  -199.1  382.22 -125.62  379.51  -75.24  382.66  -33.33  383.83
  -19.13  373.45   10.87  373.15   17.07  373.47   22.36  381.15  132.39  381.45
  200.59   380.2  208.07  376.98  218.13  380.55  225.81  380.93  361.96  382.43
  366.45   380.2  372.03  382.73  403.47  382.58  765.93  382.98 1177.22  390.66
#Mann= 9 ,-1 , 0
-1435.15    .035       0 -798.09      .1       0 -689.44    .035       0
  -75.24      .1       0  -33.33    .045       0   22.36      .1       0
  132.39    .035       0  361.96      .1       0  403.47    .035       0
#XS Ineff= 2 , 0
         -119.06           95.83
Permanent Ineff=
       F       F
Bank Sta=-33.33,22.36
XS Rating Curve= 0 ,0
Exp/Cntr=0.3,0.1

Type RM Length L Ch R = 1 ,33496   ,97.54,97.82,99.52
BEGIN DESCRIPTION:
33496
END DESCRIPTION:
#Sta/Elev= 30
-1437.57  388.52-1270.89  384.47 -803.67  381.95  -744.9  381.81  -734.7  379.81
 -719.71  382.16 -695.56  381.81 -461.92  380.55 -207.64  381.56 -134.53  379.95
   -84.4  381.47  -64.99  381.75  -55.16  382.36  -42.69   385.7  -27.23  376.71
  -15.81  373.09    5.43  372.55   17.77  373.12   39.19  381.96    44.9  385.77
   71.47  381.83  157.25  381.65  226.89  380.97  234.53  379.35  252.64  381.31
  391.66  382.13  434.05  382.26  752.72  382.91  871.45  386.24 1224.12  390.89
#Mann= 12 ,-1 , 0
-1437.57    .035       0 -803.67    .083       0 -695.56    .053       0
   -84.4      .1       0  -64.99    .087       0  -42.69    .045       0
    44.9      .1       0   71.47     .06       0  157.25    .035       0
  391.66    .068       0  434.05    .035       0 1224.12    .035       0
#XS Ineff= 2 , 0
         -119.06           95.83
Permanent Ineff=
       F       F
Bank Sta=-42.69,44.9
XS Rating Curve= 0 ,0
Exp/Cntr=0.3,0.1

Type RM Length L Ch R = 1 ,33398   ,227.28,222.42,224.4
BEGIN DESCRIPTION:
STA 33398 - CS 2
END DESCRIPTION:
#Sta/Elev= 30
   -1440  387.48 -816.65  382.28 -787.47  381.75 -612.12  381.73 -551.69  382.05
 -425.83  382.14 -202.77  380.83  -170.5  380.96 -136.28  380.25  -74.24  380.29
  -64.46  381.22  -52.06  387.58   -45.6  385.97  -22.98  372.75       0  371.95
   21.08  372.91   37.44  382.65   57.68  385.19   67.44  390.38   71.48  390.19
   94.56  382.06   129.5  381.34  175.83  381.87  339.35   381.6  625.43  382.19
  789.88  383.12  911.06   388.3 1025.59  387.07 1122.88  387.86 1271.02  391.12
#Mann= 5 ,-1 , 0
   -1440    .035       0  -74.24      .1       0  -52.06    .045       0
   67.44      .1       0   94.56    .035       0
#XS Ineff= 2 , 0
         -119.06           95.83
Permanent Ineff=
       F       F
Bank Sta=-52.06,67.44
XS Rating Curve= 0 ,0
Exp/Cntr=0.3,0.1

Type RM Length L Ch R = 1 ,33176   ,92.19,97.17,105.42
BEGIN DESCRIPTION:
STA 33176 - CS 1 - DSFLOODPL
END DESCRIPTION:
#Sta/Elev= 30
-2619.17  391.48 -2470.4   390.1-2303.79  389.74-2192.52  388.39-1661.14   385.5
-1537.23  385.52 -1237.2  384.32 -570.43  382.82  -239.2  380.94 -116.53  381.27
  -67.31  382.13  -56.18  385.23  -43.85  385.11  -15.83  372.31       0  372.25
   16.58  372.73   31.89  385.76   40.99  387.12   60.56  381.81  134.74  382.02
  230.82  380.97   294.2  381.34  466.51  381.11  528.26  381.39   711.5  383.29
  829.65  385.71  905.49  386.81  975.76  389.35 1125.87  392.34 1174.77   392.8
#Mann= 6 ,-1 , 0
-2619.17    .035       0 -116.53      .1       0  -43.85    .045       0
   31.89      .1       0   60.56    .035       0  829.65      .1       0
#XS Ineff= 2 , 0
       0 -119.06           95.83       0
Permanent Ineff=
       F       F
Bank Sta=-43.85,31.89
XS Rating Curve= 0 ,0
Exp/Cntr=0.3,0.1

Type RM Length L Ch R = 1 ,33079   ,500,500,500
BEGIN DESCRIPTION:
STA 33079 - DSXSEC
END DESCRIPTION:
#Sta/Elev= 30
-2580.66  390.62-2431.89  389.24-2265.28  388.88-2154.01  387.53-1622.63  384.64
-1498.72  384.66 -531.92  381.96 -200.69  380.08 -147.21  380.12 -146.26  380.91
  -79.46  381.11  -48.91  382.19  -34.09  386.61  -30.78  387.16  -26.18  384.72
       0  371.18   19.27  372.07   34.49  371.64    74.9  384.05   85.98  386.44
  113.08  383.47  171.27  381.82  234.99     381  580.78  381.26  749.03  383.08
  839.68  384.87  943.02   386.6 1013.29  389.14  1163.4  392.13  1212.3  392.59
#Mann= 6 ,-1 , 0
-2580.66    .035       0  -79.46      .1       0  -26.18    .045       0
   85.98      .1       0  234.99    .035       0  839.68      .1       0
#XS Ineff= 2 , 0
         -119.06           95.83
Permanent Ineff=
       F       F
Bank Sta=-26.18,85.98
XS Rating Curve= 0 ,0
Exp/Cntr=0.3,0.1
LCMann Table=0

--- CarrollCo.g03 (geometry) ---

Geom Title=PROPOSED
Program Version=5.06

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
River Reach=Reedy Creek     ,Reedy Creek

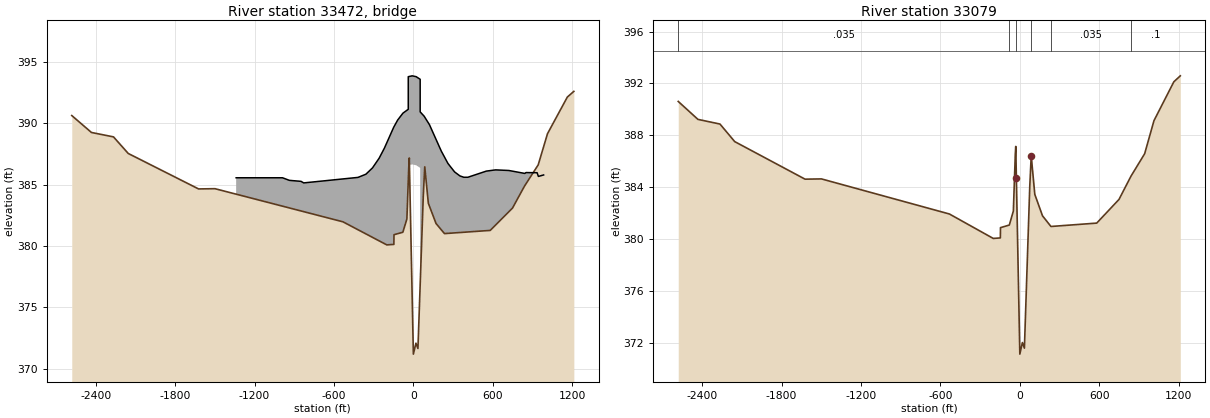
Type RM Length L Ch R = 3 ,33472   ,,,
Bridge Culvert--1,0,-1,-1, 0
Deck Dist Width WeirC Skew NumUp NumDn MinLoCord MaxHiCord MaxSubmerge Is_Ogee
99.485,29.25,2.6,0, 35, 35, , , 0.98, 0, 1.85,2,,
   -1339 -988.62 -936.86 -848.62-828.621 -418.62 -358.62 -308.62 -258.62 -218.62
 -148.62 -118.62  -78.62 -38.621  -38.62   -8.62   21.38   51.38  51.381   81.38
  121.38  211.38  261.38  311.38  351.38  381.38  411.38  551.38  621.38  721.38
  841.38  851.38  934.78  944.28   984.1
  385.55  385.55  385.34385.2584385.1317385.5798 385.841386.3574387.1456387.9717
389.6687390.2547390.8172391.1297393.7859393.8563393.7859 393.575390.9187390.5672
389.8797387.7141386.7143386.0272385.7028385.5908385.5914386.0934386.1928386.1431
385.9052385.9742  385.96  385.66  385.78
     360     360     360     360     360     360     360     360     360     360
     360     360     360     360386.5672386.6375386.5672386.3562     360     360
     360     360     360     360     360     360     360     360     360     360
     360     360     360     360     360
   -1339 -988.62 -936.86 -848.62-828.621 -418.62 -358.62 -308.62 -258.62 -218.62
 -148.62 -118.62  -78.62 -38.621  -38.62   -8.62   21.38   51.38  51.381   81.38
  121.38  211.38  261.38  311.38  351.38  381.38  411.38  551.38  621.38  721.38
  841.38  851.38  934.78  944.28   984.1
  385.55  385.55  385.34385.2584385.1317385.5798 385.841386.3574387.1456387.9717
389.6687390.2547390.8172391.1297393.7859393.8563393.7859 393.575390.9187390.5672
389.8797387.7141386.7143386.0272385.7028385.5908385.5914386.0934386.1928386.1431
385.9052385.9742  385.96  385.66  385.78
     360     360     360     360     360     360     360     360     360     360
     360     360     360     360386.5672386.6375386.5672386.3562     360     360
     360     360     360     360     360     360     360     360     360     360
     360     360     360     360     360
BR Coef=-1 , 0 , 0 ,, 0 ,,,0.8,-1,,0,
WSPro=,,,, 1 ,,,, 0 ,,,, 0 ,,,,-1 ,-1 ,-1 , 0 , 0 , 0 , 0 , 0
BC Design=,, 0 ,, 0 ,,,,,,
BC Use User HTab Curves=0
BC User HTab FreeFlow(D)= 0

Type RM Length L Ch R = 1 ,33079   ,500,500,500
BEGIN DESCRIPTION:
STA 33079 - DSXSEC
END DESCRIPTION:
#Sta/Elev= 30
-2580.66  390.62-2431.89  389.24-2265.28  388.88-2154.01  387.53-1622.63  384.64
-1498.72  384.66 -531.92  381.96 -200.69  380.08 -147.21  380.12 -146.26  380.91
  -79.46  381.11  -48.91  382.19  -34.09  386.61  -30.78  387.16  -26.18  384.72
       0  371.18   19.27  372.07   34.49  371.64    74.9  384.05   85.98  386.44
  113.08  383.47  171.27  381.82  234.99     381  580.78  381.26  749.03  383.08
  839.68  384.87  943.02   386.6 1013.29  389.14  1163.4  392.13  1212.3  392.59
#Mann= 6 ,-1 , 0
-2580.66    .035       0  -79.46      .1       0  -26.18    .045       0
   85.98      .1       0  234.99    .035       0  839.68      .1       0
#XS Ineff= 2 , 0
         -119.06           95.83
Permanent Ineff=
       F       F
Bank Sta=-26.18,85.98
XS Rating Curve= 0 ,0
Exp/Cntr=0.3,0.1
LCMann Table=0